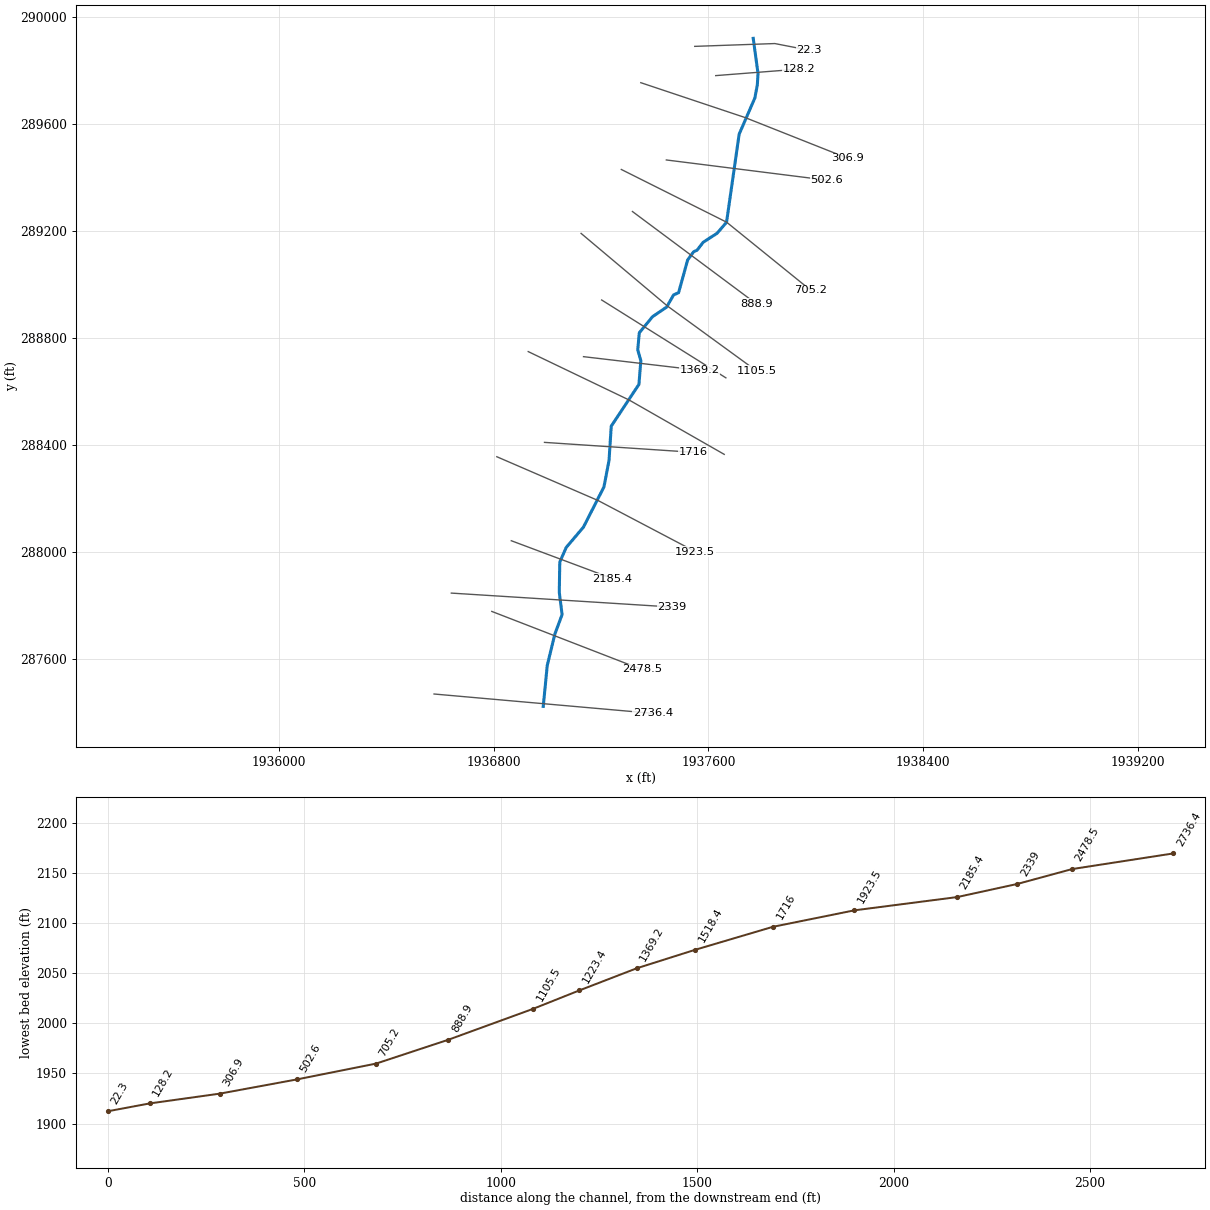
--- BrmmrBrnch.prj (project) ---

Proj Title=BrmmrBrnch
Current Plan=p01
Default Exp/Contr=0,0
English Units
Geom File=g01
Flow File=f01
Plan File=p01
BEGIN DESCRIPTION:
END DESCRIPTION:
DSS Export Rating Curves= 0
DSS Export Rating Curve Sorted= 0
DSS Export Volume Flow Curves= 0
DXF OffsetX= 0
DXF OffsetY= 0
DXF ScaleX= 0
DXF ScaleY= 0

--- BrmmrBrnch.p01 (plan) ---

Plan Title=Floodplain
Program Version=4.00
Geom File=g01
Flow File=f01
K Sum by GR=0
Std Step Tol=0.01
Critical Tol=0.01
Num of Std Step Trials=20
Max Error Tol=0.3
Flow Tol Ratio=0.001
Split Flow NTrial=30
Split Flow Tol=0.02
Split Flow Ratio=0.02
Log Output Level=0
Friction Slope Method=1
Unsteady Friction Slope Method=2
Unsteady Bridges Friction Slope Method=1
Global Log Level=0
CheckData=False
Run HTab=0
Run UNet=0
Run PostProcess=0
UNET Theta=0
UNET Theta Warmup=0
UNET ZTol=0
UNET ZSATol=0
UNET MxIter=0
UNET MaxInSteps=0
UNET DtIC=0
UNET DtMin=0
UNET MaxCRTS=0
UNET WFStab=0
UNET SFStab=0
UNET WFX=0
UNET SFX=0
UNET DSS MLevel=0
UNET DZMax Abort=0
UNET Convert EG Bridges=0
UNET Use Existing IB Tables=0
UNET Froude Limit=0
UNET Froude Power=0
Write IC File=0
Echo Input=False
Echo Output=False
Write Detailed=0

--- BrmmrBrnch.f01 (steady flow) ---

Flow Title=NFF Regression Equation
Program Version=4.00
Number of Profiles=1
Profile Names=P100yr
River Rch & RM=BrmmrBrnch,Main      ,2736.4
508.8166
River Rch & RM=BrmmrBrnch,Main      ,1923.5
539.7373
River Rch & RM=BrmmrBrnch,Main      ,128.2
592.3183
Boundary for River Rch & Prof#=BrmmrBrnch,Main      ,1
Up Type=0
Dn Type=3
Dn Slope=0.065368

--- BrmmrBrnch.g01 (geometry) ---

Geom Title=USGS 3m DEM
Program Version=4.10

River Reach=BrmmrBrnch      ,Main
Reach XY= 30
     1936984.348      287424.422     1936999.128      287576.927
     1937027.634      287694.599     1937054.532      287767.222
     1937044.009      287850.446     1937045.923      287963.325
     1937069.838      288017.851     1937133.947      288093.605
     1937210.461      288243.877     1937229.519      288343.247
     1937237.658      288470.988     1937340.905      288626.862
     1937348.007      288715.622     1937336.488       288755.85
     1937342.301      288819.799     1937391.725      288880.026
     1937443.927      288915.406     1937470.096      288961.208
     1937488.689      288969.449      1937522.52      289091.871
     1937544.611      289122.101     1937557.661      289128.242
     1937580.248      289157.605      1937632.35       289191.47
     1937667.398      289232.359     1937714.413       289561.39
     1937773.029      289696.853     1937782.147      289745.047
     1937784.753       289788.03     1937766.863      289919.416

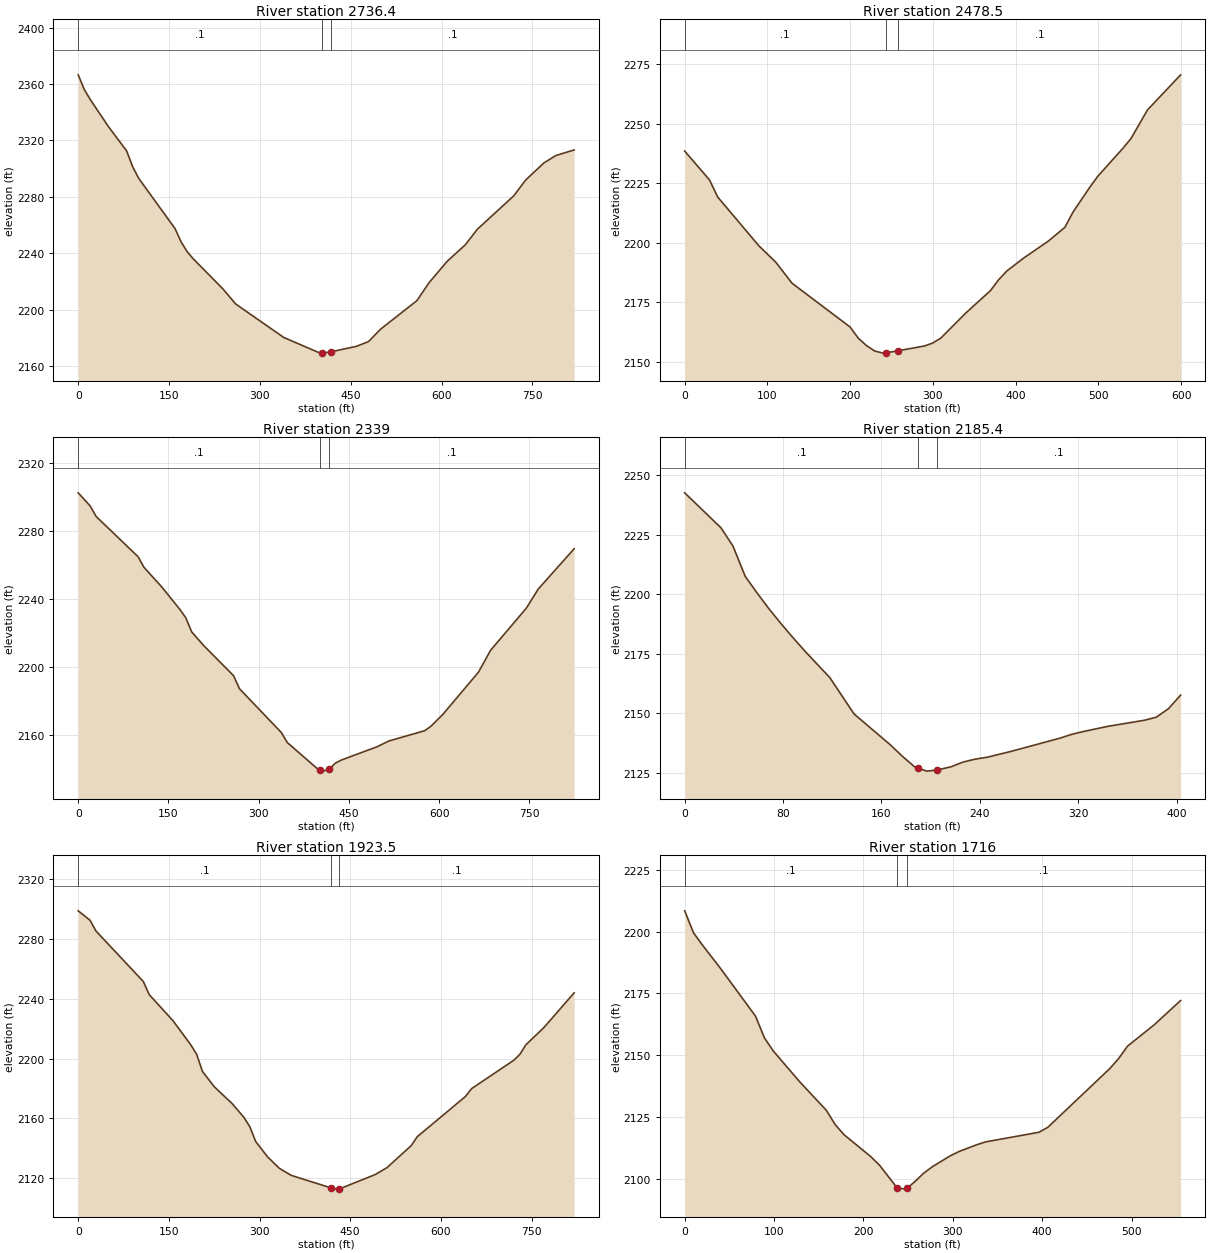
Type RM Length L Ch R = 1 ,2736.4  ,264.2,257.8,251.5
XS GIS Cut Line= 3
     1936577.332      287470.552     1936985.232      287434.383
     1937393.131      287398.214
#Sta/Elev= 30
       0 2366.49      10 2356.12      20 2348.94    49.9 2329.82    79.9 2312.64
    89.9  2301.4    99.9 2293.16   159.8 2257.61   169.8 2248.23   179.8 2241.28
   189.8 2236.21   239.7 2214.47   259.7 2204.23   339.6 2180.36   399.5  2169.3
     402 2169.34     417  2170.2   459.4 2174.11   479.4 2177.46   499.4 2186.29
   559.3 2206.48   579.3 2219.15   609.3 2234.35   639.2 2246.04   659.2  2257.1
   719.1 2280.68   739.1 2292.02   769.1  2304.1     789 2309.33     819 2313.27
#Mann= 3 , 0 , 0
       0      .1       0     402    .045       0     417      .1       0
Bank Sta=402,417
XS Rating Curve= 0 ,0
Exp/Cntr=0.3,0.1

Type RM Length L Ch R = 1 ,2478.5  ,132.7,139.6,146.4
XS GIS Cut Line= 2
     1936792.518         287779.     1937351.173       287562.17
#Sta/Elev= 30
       0 2238.54      30 2226.43      40  2219.2    89.9 2198.67   109.9 2191.95
   129.8 2183.04   199.8 2164.69   209.7 2160.01   219.7 2156.87   229.7 2154.58
   239.7  2153.7     243 2153.81     258  2154.7   289.6 2156.69   299.6  2157.9
   309.6 2160.03   339.6 2170.51   369.5 2179.94   379.5 2184.56   389.5 2188.24
   409.5 2193.58   439.5 2200.75   459.4 2206.49   469.4 2212.99   489.4 2223.28
   499.4 2228.03   529.3  2239.6   539.3 2243.78   559.3 2255.82   599.3 2270.55
#Mann= 3 , 0 , 0
       0      .1       0     243    .045       0     258      .1       0
Bank Sta=243,258
XS Rating Curve= 0 ,0
Exp/Cntr=0.3,0.1

Type RM Length L Ch R = 1 ,2339    ,160,153.3,146.7
XS GIS Cut Line= 2
     1936641.686      287847.452     1937464.627      287795.356
#Sta/Elev= 30
       0 2302.33    19.9 2294.61    29.8 2288.44    99.4 2264.85   109.3 2258.59
   139.1 2246.98   168.9  2233.9   178.8 2228.98   188.8 2220.59   208.6 2212.65
   258.3 2194.91   268.2 2187.23   337.8 2161.51   347.7 2155.64   397.4 2140.35
   401.8 2139.69   407.3 2138.86   416.8 2139.89   427.2 2143.43   437.1 2145.32
   496.7 2153.15   516.6 2156.56   576.2 2162.62   586.2 2165.14     606 2172.07
   665.6 2197.01   685.5 2209.76   745.1 2234.59     765 2245.85   824.6 2269.48
#Mann= 3 , 0 , 0
       0      .1       0   401.8    .045       0   416.8      .1       0
Bank Sta=401.8,416.8
XS Rating Curve= 0 ,0
Exp/Cntr=0.3,0.1

Type RM Length L Ch R = 1 ,2185.4  ,262.9,261.8,258.9
XS GIS Cut Line= 2
      1936865.22      288043.022     1937242.758      287901.445
#Sta/Elev= 30
       0 2242.62    29.5 2227.94    39.3 2220.24    49.2 2207.57      59 2200.48
    68.8 2193.75    78.7 2187.45    88.5 2181.54    98.3 2175.86     118 2165.03
   137.7 2149.77   167.2  2136.8     177 2131.98   186.8 2127.64   189.8 2127.07
   196.7 2125.76   204.8  2126.2   216.4 2127.56   226.2 2129.55     236 2130.77
   245.9 2131.59   265.5 2134.07   304.9 2139.57   314.7 2141.21   324.5 2142.43
   344.2 2144.58   373.7 2147.11   383.5 2148.42   393.4 2152.02   403.2 2157.67
#Mann= 3 , 0 , 0
       0      .1       0   189.8    .045       0   204.8      .1       0
Bank Sta=189.8,204.8
XS Rating Curve= 0 ,0
Exp/Cntr=0.3,0.1

Type RM Length L Ch R = 1 ,1923.5  ,199.8,207.5,216.9
XS GIS Cut Line= 3
     1936811.174      288356.796     1937188.507      288193.281
     1937550.536       288002.56
#Sta/Elev= 30
       0 2298.94    19.6  2292.6    29.4  2285.4   107.7 2251.62   117.5  2242.8
   156.7 2225.38     186 2209.32   195.8 2202.95   205.6 2191.32   225.2 2181.03
   254.6 2169.85   274.2 2160.57     284 2154.23   293.7 2144.35   313.3 2134.13
   332.9 2126.43   352.5 2121.74   418.7 2113.29   431.2 2112.53   491.1 2122.24
     511 2126.98     551 2141.72   560.9 2147.66   640.8 2174.65   650.8 2179.85
   720.6 2198.86   730.6 2202.82   740.6 2209.22   770.5 2220.82   820.4 2244.02
#Mann= 3 , 0 , 0
       0      .1       0   418.7    .045       0   431.2      .1       0
Bank Sta=418.7,431.2
XS Rating Curve= 0 ,0
Exp/Cntr=0.3,0.1

Type RM Length L Ch R = 1 ,1716    ,205.8,197.6,188.2
XS GIS Cut Line= 2
      1936988.94      288410.356     1937542.493      288373.368
#Sta/Elev= 30
       0 2208.34     9.9 2199.48    19.8 2194.56    39.6 2185.36    79.3 2165.84
    89.2  2157.1    99.1 2151.83   128.8 2139.34   158.5 2127.89   168.4 2122.11
   178.3 2118.04     208 2109.28     218 2105.74   237.8 2096.55   247.7  2096.1
   248.9 2096.47   257.6 2099.17   267.5 2102.56   277.4 2105.21   297.2 2109.56
   307.1  2111.3   326.9 2114.03   336.8 2115.16   396.3 2119.03   406.2 2121.02
   475.5 2144.69   485.4 2148.74   495.4 2153.75   525.1 2162.33   554.8 2172.17
#Mann= 3 , 0 , 0
       0      .1       0   237.8    .045       0   248.9      .1       0
Bank Sta=237.8,248.9
XS Rating Curve= 0 ,0
Exp/Cntr=0.3,0.1

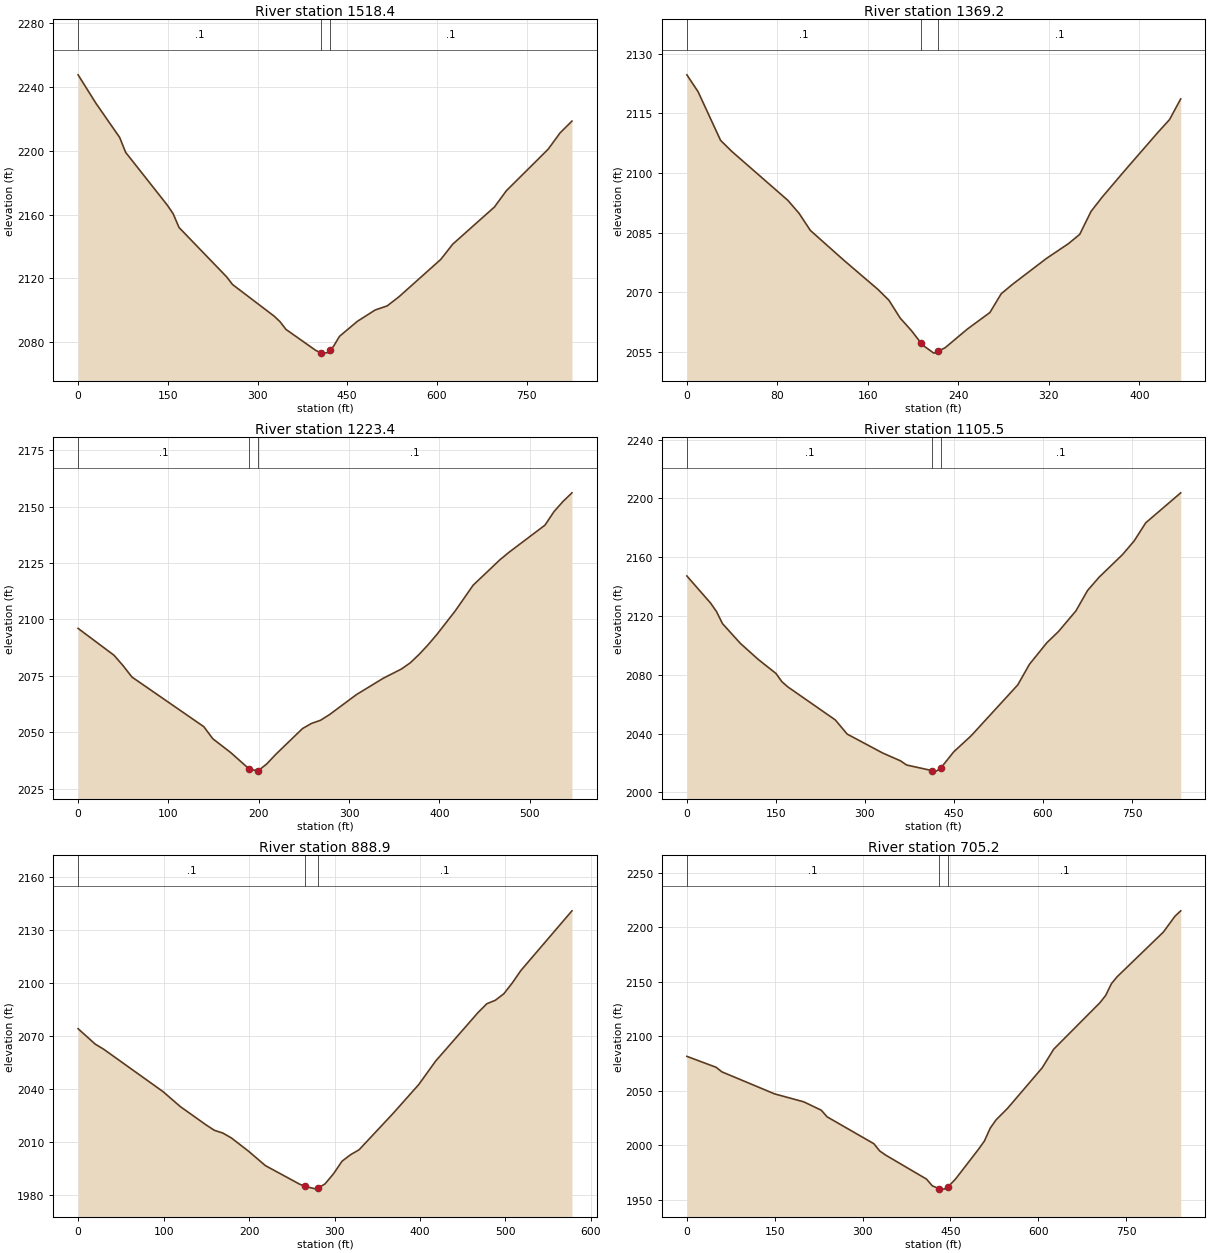
Type RM Length L Ch R = 1 ,1518.4  ,141.5,149.1,158.2
XS GIS Cut Line= 3
     1936928.232      288749.469     1937304.166      288568.677
     1937658.815        288365.6
#Sta/Elev= 30
       0 2247.49    29.8 2229.68    69.5 2208.28    79.5 2198.95     149 2165.97
   158.9 2160.54   168.8 2151.88   248.3 2121.02   258.2  2116.2   327.8  2096.4
   337.7 2092.89   347.6 2088.08   397.3 2074.96   406.4 2073.37   407.2 2073.23
   417.2 2073.52   421.4  2075.2   427.1 2077.47   437.1 2083.75     467 2093.15
   496.9 2100.27   516.8  2102.8   536.8  2108.6   606.5 2131.94   626.5 2141.48
   696.2 2164.73   716.2 2174.95     786 2200.91   805.9 2211.12   825.8 2218.52
#Mann= 3 , 0 , 0
       0      .1       0   406.4    .045       0   421.4      .1       0
Bank Sta=406.4,421.4
XS Rating Curve= 0 ,0
Exp/Cntr=0.3,0.1

Type RM Length L Ch R = 1 ,1369.2  ,156.5,145.9,135.4
XS GIS Cut Line= 2
     1937134.343      288730.498     1937568.002       288679.48
#Sta/Elev= 30
       0 2124.65     9.9 2120.42    29.8 2108.19    39.7 2105.42    89.3 2093.12
    99.2 2089.86   109.2 2085.56   138.9 2078.05   168.7 2070.81   178.6 2068.04
   188.6 2063.55   198.5 2060.41   207.1 2057.26   208.4 2056.78   218.3 2054.75
   222.1 2055.26   228.2 2056.08   248.1 2060.82   267.9 2064.95   277.9 2069.67
   287.8 2072.01   317.6 2078.47   337.4 2082.26   347.3 2084.58   357.3 2090.34
   367.2 2093.95     387 2100.57   416.8 2110.31   426.7  2113.4   436.6 2118.61
#Mann= 3 , 0 , 0
       0      .1       0   207.1    .045       0   222.1      .1       0
Bank Sta=207.1,222.1
XS Rating Curve= 0 ,0
Exp/Cntr=0.3,0.1

Type RM Length L Ch R = 1 ,1223.4  ,120.4,117.2,115.6
XS GIS Cut Line= 2
     1937201.943      288942.226     1937664.938      288651.419
#Sta/Elev= 30
       0 2095.98    39.8 2084.07    49.7 2079.51    59.6 2074.43   139.2 2052.41
   149.1 2047.08     169 2040.93   188.9 2033.85   198.8 2032.71   208.8 2035.87
   218.7 2040.08   248.5 2051.59   258.5 2053.87   268.4 2055.25   278.3 2057.75
   308.2 2066.64     338 2073.91   357.9 2077.96   367.8 2080.73   377.8 2084.55
   387.7  2088.8   397.6 2093.48   417.5 2103.71   437.4 2115.14   467.2 2126.47
   477.2 2129.76   516.9 2141.75   526.9 2147.75   536.8 2152.22   546.8 2156.09
#Mann= 3 , 0 , 0
       0      .1       0   188.9    .045       0   198.8      .1       0
Bank Sta=188.9,198.8
XS Rating Curve= 0 ,0
Exp/Cntr=0.3,0.1

Type RM Length L Ch R = 1 ,1105.5  ,214.2,216.4,216.9
XS GIS Cut Line= 3
     1937125.347      289190.872     1937446.589      288920.066
     1937779.323      288677.236
#Sta/Elev= 30
       0 2147.24      40 2128.78      50 2122.97      60 2114.83      90 2101.42
     120 2090.54   150.1 2080.92   160.1  2075.3   170.1 2071.76   250.1 2049.28
   270.1 2039.64   330.1 2026.73   360.1 2021.41   370.1 2018.63   412.7 2014.82
   420.2 2014.44   427.7 2016.46   449.6 2027.56     479  2038.5   557.5 2073.11
   577.1 2087.08   606.5 2101.79   626.1 2109.42   655.5 2123.48   675.2 2137.42
   694.8 2146.49     734 2161.79   753.6 2171.06   773.2 2183.44   832.1 2203.82
#Mann= 3 , 0 , 0
       0      .1       0   412.7    .045       0   427.7      .1       0
Bank Sta=412.7,427.7
XS Rating Curve= 0 ,0
Exp/Cntr=0.3,0.1

Type RM Length L Ch R = 1 ,888.9   ,179.8,183.7,182.8
XS GIS Cut Line= 2
     1937316.735      289272.572      1937779.73       288926.92
#Sta/Elev= 30
       0 2074.19    19.9 2065.54    29.9 2062.61    99.6 2038.55   119.5 2030.21
   149.4 2019.94   159.4 2016.79   169.4  2015.2   179.3 2012.47   199.2 2005.04
   219.2  1996.8     259 1986.37   265.3 1985.14   278.9 1983.53   280.3 1983.95
   288.9  1986.5   298.9 1992.26   308.8 1999.32   318.8 2002.99   328.7 2005.76
   368.6 2026.36   398.5 2042.61   418.4 2055.96   468.2 2083.48   478.2 2088.31
   488.1 2090.26   498.1 2093.94   508.1 2100.14     518 2107.06   577.8 2140.82
#Mann= 3 , 0 , 0
       0      .1       0   265.3    .045       0   280.3      .1       0
Bank Sta=265.3,280.3
XS Rating Curve= 0 ,0
Exp/Cntr=0.3,0.1

Type RM Length L Ch R = 1 ,705.2   ,194.6,202.6,215.5
XS GIS Cut Line= 3
     1937275.302       289429.64     1937667.734      289232.751
     1937981.657      288978.078
#Sta/Elev= 30
       0 2081.53    49.9 2071.52    59.9  2067.3   149.7 2047.14   199.6 2039.84
   229.5 2032.15   239.5 2026.08   319.3 2001.43   329.3 1994.79   339.3 1991.04
   409.1 1969.02   419.1 1962.81   431.3 1960.09     439 1959.79   446.3 1962.01
   458.8 1969.08   498.2 1996.49   508.1 2003.94   517.9 2015.62   527.8 2023.19
   547.5 2033.81   606.7    2071   626.4 2088.09   705.3  2130.7   715.1 2137.37
     725 2148.18   734.8 2154.58   813.7 2195.52   833.4    2210   843.3 2214.98
#Mann= 3 , 0 , 0
       0      .1       0   431.3    .045       0   446.3      .1       0
Bank Sta=431.3,446.3
XS Rating Curve= 0 ,0
Exp/Cntr=0.3,0.1

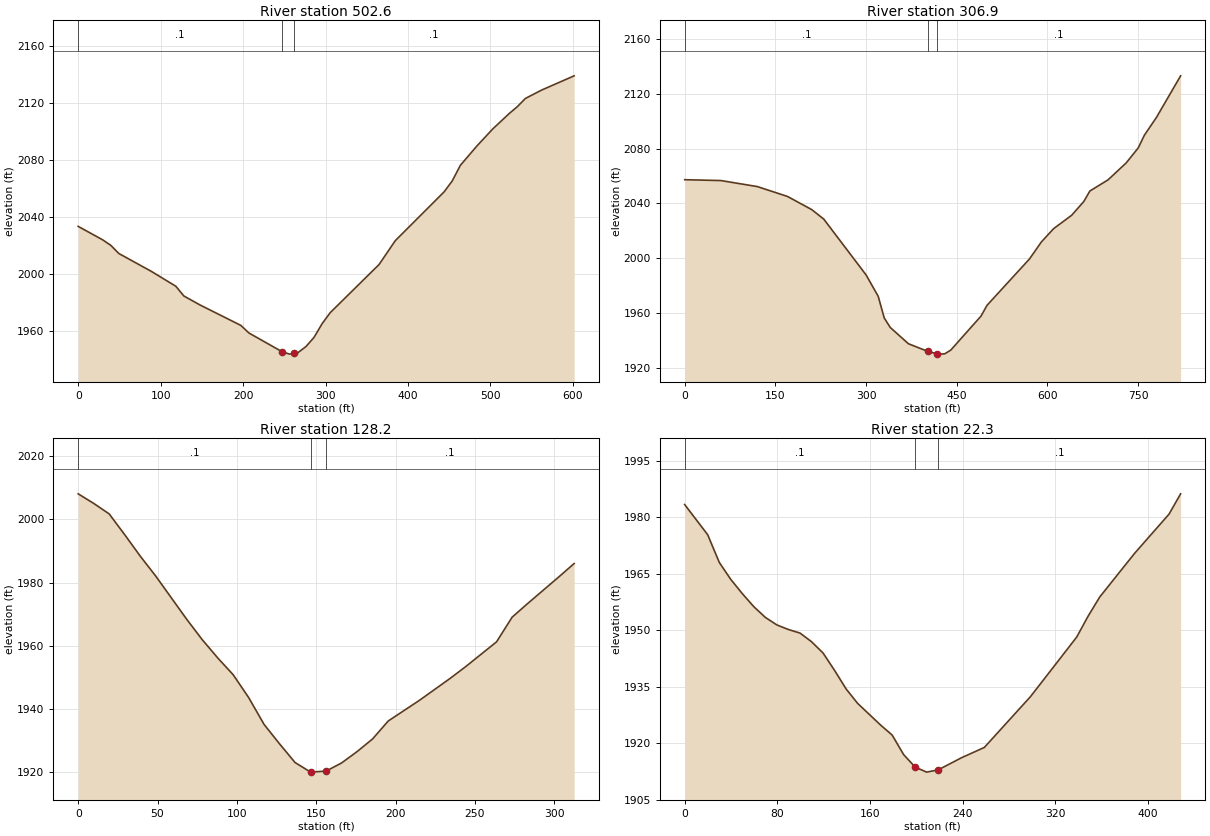
Type RM Length L Ch R = 1 ,502.6   ,200.2,195.6,189.9
XS GIS Cut Line= 2
     1937443.006      289465.168     1938039.925      289389.915
#Sta/Elev= 30
       0 2033.47    29.6 2024.07    39.4 2020.24    49.3 2014.46    88.8 2001.91
   118.4 1991.51   128.2 1984.67     148 1978.32   197.3 1964.06   207.1 1958.74
   247.1 1945.69   256.4 1943.93   262.1 1944.46   266.3 1944.85   276.2  1949.2
     286 1955.61   295.9 1965.31   305.8 1973.06   364.9 2006.71   384.7 2023.51
   443.8 2057.63   453.7 2065.32   463.6 2076.28   483.3  2089.6     503 2101.85
   522.7  2112.5   532.6 2117.34   542.5 2123.15   562.2 2129.03   601.6    2139
#Mann= 3 , 0 , 0
       0      .1       0   247.1    .045       0   262.1      .1       0
Bank Sta=247.1,262.1
XS Rating Curve= 0 ,0
Exp/Cntr=0.3,0.1

Type RM Length L Ch R = 1 ,306.9   ,169.4,178.6,189
XS GIS Cut Line= 3
      1937347.81      289753.775     1937736.667      289623.521
      1938117.87      289472.006
#Sta/Elev= 30
       0 2057.21      60 2056.59     120 2052.21     170    2045     210 2035.42
     230 2028.47   300.1 1987.64   320.1 1972.06   330.1  1956.2   340.1 1949.26
   370.1  1937.4   402.6 1931.74   417.6 1930.05   420.1 1929.81   430.1 1930.03
   440.1 1932.75   490.1 1957.55   500.1 1965.47   570.2 1999.26   590.2 2011.86
   610.2 2021.44   640.2 2031.28   660.2 2041.29   670.2 2048.96   700.2 2057.08
   730.3 2069.48   750.3  2080.5   760.3 2089.66   780.3 2102.69   820.3 2133.09
#Mann= 3 , 0 , 0
       0      .1       0   402.6    .045       0   417.6      .1       0
Bank Sta=402.6,417.6
XS Rating Curve= 0 ,0
Exp/Cntr=0.3,0.1

Type RM Length L Ch R = 1 ,128.2   ,106.9,105.9,104.9
XS GIS Cut Line= 2
     1937627.163       289780.19     1937938.767      289804.607
#Sta/Elev= 28
       0 2008.09     9.8 2005.05    19.5 2001.75    29.3 1995.17    39.1 1988.38
    48.8 1982.12    68.4  1968.4    78.1    1962    87.9  1956.2    97.7 1950.85
   107.4 1943.67   117.2 1935.11     127 1928.94   136.7 1923.08   146.5 1920.05
   156.3 1920.38     166 1922.95   175.8 1926.55   185.6 1930.57   195.4 1936.22
   214.9  1942.7   234.4 1949.69   244.2 1953.41   263.7 1961.27   273.5 1969.06
   283.3 1973.39   302.8 1981.75   312.6 1986.04
#Mann= 3 , 0 , 0
       0      .1       0   146.5    .045       0   156.3      .1       0
Bank Sta=146.5,156.3
XS Rating Curve= 0 ,0
Exp/Cntr=0.3,0.1

Type RM Length L Ch R = 1 ,22.3    ,22.6,22.3,22
XS GIS Cut Line= 3
     1937548.905      289889.415     1937847.364      289899.938
     1937974.592      289875.066
#Sta/Elev= 30
       0 1983.33    19.9 1975.31    29.9 1967.96    39.8 1963.46    49.8 1959.67
    59.7 1956.22    69.7 1953.36    79.6 1951.37    89.6 1950.15    99.6 1949.21
   109.5 1946.93   119.5 1943.91   129.4 1939.32   139.4 1934.38   149.3 1930.56
   169.2 1924.78   179.2 1922.12   189.1 1916.93   199.1  1913.6     209 1912.28
     219 1912.89   238.9 1916.07   258.8 1918.84   298.6 1932.31   338.5 1948.12
   348.5 1953.74   358.5  1958.8   388.4 1970.32   418.3 1980.79   428.3 1986.18
#Mann= 3 , 0 , 0
       0      .1       0   199.1    .045       0     219      .1       0
Bank Sta=199.1,219
XS Rating Curve= 0 ,0
Exp/Cntr=0.3,0.1

Chan Stop Cuts=-1
Use User Specified Reach Order=0
Composite Channel Slope=5